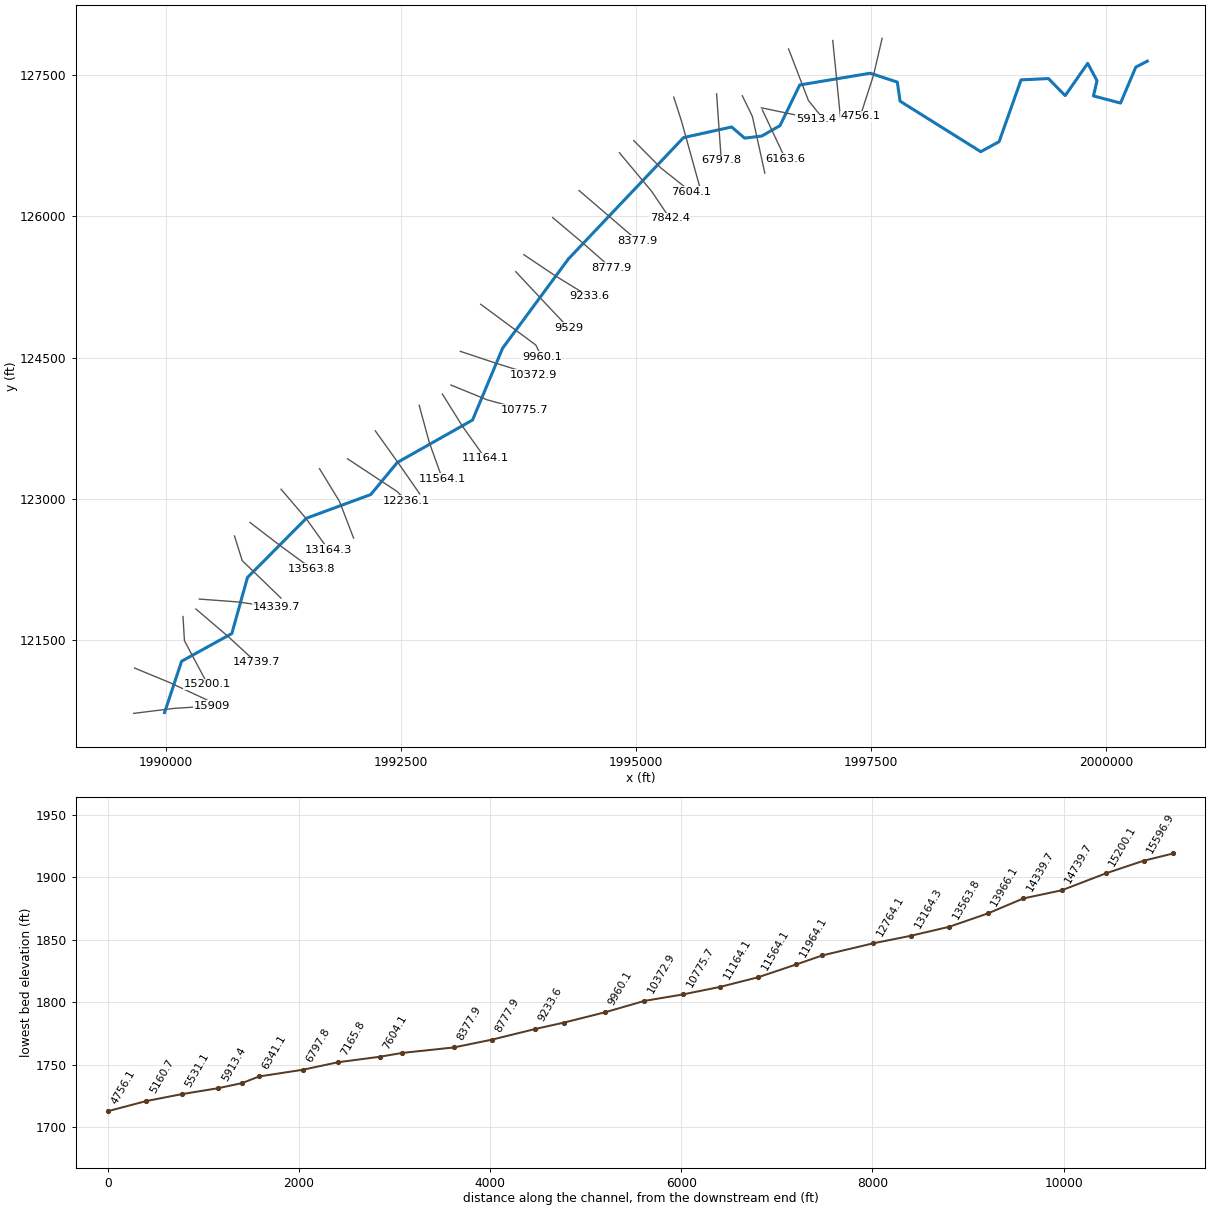
--- BgSprngBr.prj (project) ---

Proj Title=BgSprngBr
Current Plan=p01
Default Exp/Contr=0,0
English Units
Geom File=g01
Flow File=f01
Plan File=p01
BEGIN DESCRIPTION:
END DESCRIPTION:
DSS Export Rating Curves= 0
DSS Export Rating Curve Sorted= 0
DSS Export Volume Flow Curves= 0
DXF OffsetX= 0
DXF OffsetY= 0
DXF ScaleX= 0
DXF ScaleY= 0

--- BgSprngBr.p01 (plan) ---

Plan Title=Floodplain
Program Version=4.00
Geom File=g01
Flow File=f01
K Sum by GR=0
Std Step Tol=0.01
Critical Tol=0.01
Num of Std Step Trials=20
Max Error Tol=0.3
Flow Tol Ratio=0.001
Split Flow NTrial=30
Split Flow Tol=0.02
Split Flow Ratio=0.02
Log Output Level=0
Friction Slope Method=1
Unsteady Friction Slope Method=2
Unsteady Bridges Friction Slope Method=1
Global Log Level=0
CheckData=False
Run HTab=0
Run UNet=0
Run PostProcess=0
UNET Theta=0
UNET Theta Warmup=0
UNET ZTol=0
UNET ZSATol=0
UNET MxIter=0
UNET MaxInSteps=0
UNET DtIC=0
UNET DtMin=0
UNET MaxCRTS=0
UNET WFStab=0
UNET SFStab=0
UNET WFX=0
UNET SFX=0
UNET DSS MLevel=0
UNET DZMax Abort=0
UNET Convert EG Bridges=0
UNET Use Existing IB Tables=0
UNET Froude Limit=0
UNET Froude Power=0
Write IC File=0
Echo Input=False
Echo Output=False
Write Detailed=0

--- BgSprngBr.f01 (steady flow) ---

Flow Title=NFF Regression Equation
Program Version=4.00
Number of Profiles=1
Profile Names=P100yr
River Rch & RM=BgSprngBr,Main      ,15909
665.2071
River Rch & RM=BgSprngBr,Main      ,12236.1
709.5150
River Rch & RM=BgSprngBr,Main      ,11164.1
786.8461
River Rch & RM=BgSprngBr,Main      ,9233.6
805.4152
River Rch & RM=BgSprngBr,Main      ,8777.9
1079.741
River Rch & RM=BgSprngBr,Main      ,6341.1
1107.185
River Rch & RM=BgSprngBr,Main      ,6163.6
1289.943
River Rch & RM=BgSprngBr,Main      ,325.4
1327.661
Boundary for River Rch & Prof#=BgSprngBr,Main      ,1
Up Type=0
Dn Type=3
Dn Slope=0.049643

--- BgSprngBr.g01 (geometry) ---

Geom Title=USGS 3m DEM
Program Version=4.10

River Reach=BgSprngBr       ,Main
Reach XY= 30
     1989986.301      120727.576     1990167.713      121272.986
     1990701.834      121567.895     1990867.806      122163.144
     1991494.186      122793.006     1992178.824      123044.981
     1992460.791      123385.649     1993260.705      123836.806
     1993580.181      124599.981     1994278.499      125547.107
     1995504.048      126838.698     1996014.761      126951.506
      1996153.61      126832.927     1996335.751      126855.106
     1996529.576      126965.863     1996739.132      127397.819
     1997488.926      127522.661     1997776.717      127428.304
     1997806.176      127225.675     1998663.682      126688.773
      1998858.79      126795.146     1999091.831      127451.893
     1999383.161      127466.047     1999561.261      127284.408
     1999800.695      127627.635      1999899.77      127442.457
     1999861.832      127281.482     2000149.819      127205.383
     2000312.331      127587.993      2000434.93      127650.987

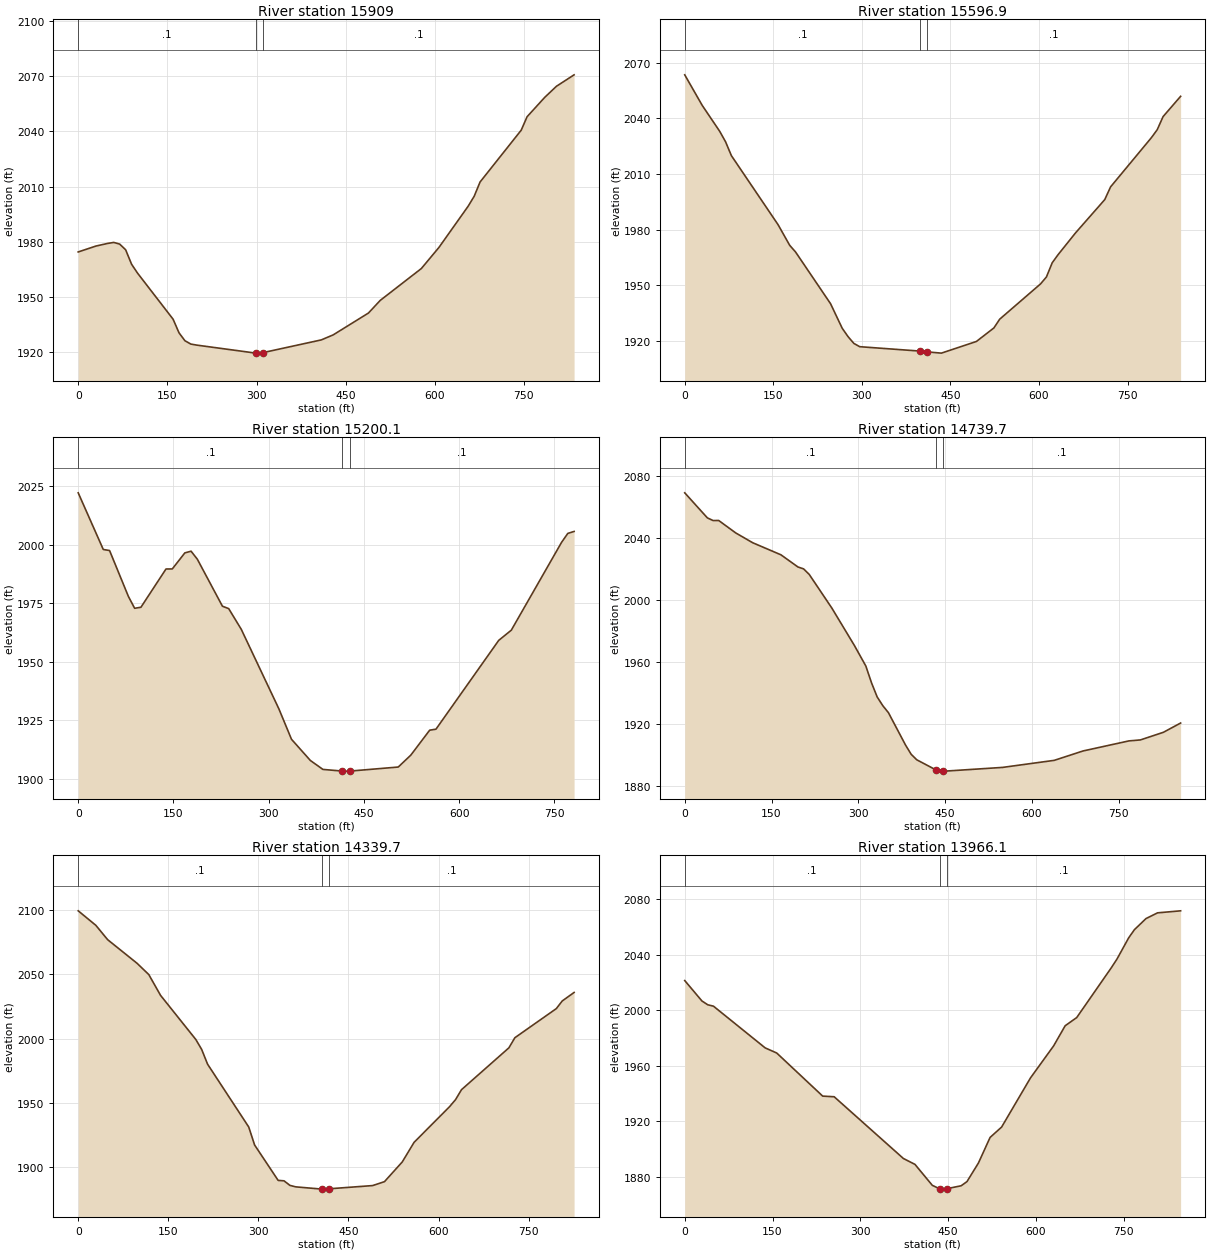
Type RM Length L Ch R = 1 ,15909   ,323.1,312.1,299.9
XS GIS Cut Line= 3
     1989658.626      120719.185     1990084.449      120771.919
     1990488.904       120798.33
#Sta/Elev= 30
       0 1974.36    29.9 1977.58    49.9 1979.03    59.9 1979.55    69.8 1978.63
    79.8 1975.56    89.8 1967.68    99.8 1962.84   159.7  1937.7   169.6 1930.31
   179.6 1925.97   189.6 1924.16   199.6 1923.59   298.5 1919.25   299.4 1919.23
   310.5 1919.47   409.1 1926.44   429.1 1929.18   488.4 1941.08   508.2 1947.96
   577.4 1965.33     607 1976.83   656.4  1999.4   666.3 2004.72   676.2 2012.48
   745.4 2040.71   755.3 2048.04     785  2058.6   804.7 2064.64   834.4 2070.88
#Mann= 3 , 0 , 0
       0      .1       0   298.5    .045       0   310.5      .1       0
Bank Sta=298.5,310.5
XS Rating Curve= 0 ,0
Exp/Cntr=0.3,0.1

Type RM Length L Ch R = 1 ,15596.9 ,411.4,396.7,383.1
XS GIS Cut Line= 3
     1989667.862      121200.974     1990042.144      121046.169
     1990436.327      120862.595
#Sta/Elev= 30
       0 2063.42    29.6 2046.95    59.3 2032.92    69.2 2027.28      79 2019.85
   158.1 1982.61   177.8 1971.48   187.7 1967.89     247 1939.99   266.7 1926.78
   276.6 1922.25   286.5 1918.58   296.4 1916.82   398.8 1914.44   410.8 1914.01
   434.7 1913.35     494 1919.64   523.6 1926.92   533.5 1931.66   602.7 1950.69
   612.6 1954.41   622.4 1962.06   632.3 1966.42     662 1978.22   711.4 1996.13
   721.3 2003.01   790.4 2029.53   800.3 2033.84   810.2  2040.9   839.9 2051.83
#Mann= 3 , 0 , 0
       0      .1       0   398.8    .045       0   410.8      .1       0
Bank Sta=398.8,410.8
XS Rating Curve= 0 ,0
Exp/Cntr=0.3,0.1

Type RM Length L Ch R = 1 ,15200.1 ,451.7,460,467.4
XS GIS Cut Line= 3
     1990182.551      121748.153     1990197.825       121491.73
     1990444.354      121028.994
#Sta/Elev= 30
       0 2022.12    39.5 1997.91    49.4 1997.47      79  1977.9    88.9 1972.79
    98.8 1973.23   138.3 1989.58   148.2  1989.6     168 1996.46   177.8 1997.18
   187.7 1993.75   227.2 1973.68   237.1 1972.64   256.9  1963.8   316.2 1929.79
     336 1916.83   365.7 1907.78   385.5 1903.95   416.3 1903.24     425 1903.22
   428.3 1903.24   504.2 1904.97     524 1910.06   553.7 1920.71   563.6 1921.14
   662.5 1959.09   682.3 1963.44   761.4 2000.93   771.3 2004.78   781.2 2005.62
#Mann= 3 , 0 , 0
       0      .1       0   416.3    .045       0   428.3      .1       0
Bank Sta=416.3,428.3
XS Rating Curve= 0 ,0
Exp/Cntr=0.3,0.1

Type RM Length L Ch R = 1 ,14739.7 ,387.1,400.3,413
XS GIS Cut Line= 3
      1990319.91       121828.06     1990655.004      121542.838
     1990961.498      121260.497
#Sta/Elev= 30
       0 2069.14    39.1 2052.99    48.9 2051.28    58.7  2051.3      88 2043.31
   117.4 2036.96   166.2 2029.18   195.6 2021.33   205.4 2020.09   215.1 2016.53
   254.2 1994.82   293.4 1970.54   312.9 1957.47   322.7 1946.66   332.5 1937.52
   342.3 1931.86     352 1927.35   381.4 1906.57   391.2 1900.57   400.9    1897
     434 1890.49     446 1889.72     450 1889.69   549.2 1892.09   638.5 1896.64
   688.1 1902.68   767.5 1909.18   787.3 1909.81     827 1914.72   856.8  1920.7
#Mann= 3 , 0 , 0
       0      .1       0     434    .045       0     446      .1       0
Bank Sta=434,446
XS Rating Curve= 0 ,0
Exp/Cntr=0.3,0.1

Type RM Length L Ch R = 1 ,14339.7 ,388.4,373.6,360.2
XS GIS Cut Line= 3
      1990356.54      121933.946     1990766.639      121903.467
     1991176.923      121845.139
#Sta/Elev= 30
       0 2099.02    29.4 2087.76      49 2076.66    97.9 2058.37   117.5 2049.61
   137.1 2033.47   195.8 1999.26   205.6  1991.5   215.4  1980.1   283.9  1931.4
   293.7 1917.42   332.9 1889.99   342.7 1889.64   352.5 1886.11   362.3 1884.96
   405.2 1883.24   411.2 1883.21   417.2 1883.45   490.2 1885.96   509.9    1889
   539.5 1904.28   559.2 1919.49   618.4 1947.21   628.3 1952.65   638.2 1960.35
   717.1  1992.8     727 2000.61     796 2023.19   805.9 2029.14   825.6 2035.71
#Mann= 3 , 0 , 0
       0      .1       0   405.2    .045       0   417.2      .1       0
Bank Sta=405.2,417.2
XS Rating Curve= 0 ,0
Exp/Cntr=0.3,0.1

Type RM Length L Ch R = 1 ,13966.1 ,399.7,402.2,405.1
XS GIS Cut Line= 3
     1990730.048      122604.391      1990812.17      122342.057
     1991223.952      121944.987
#Sta/Elev= 30
       0 2021.31    29.4 2006.59    39.3 2003.87    49.1 2002.85   137.4 1972.82
   157.1 1969.14   235.6 1938.11   255.2 1937.65   373.5 1893.17   393.2 1888.96
   422.8 1873.88   435.5 1871.33   442.6 1871.14   447.5 1871.44   472.1 1873.56
     482 1876.54   501.7 1890.03   521.5 1908.36   541.2 1915.83   590.5 1951.22
     630 1974.26   649.7 1988.76   669.4 1994.64   728.6 2030.57   738.4 2036.91
   758.2 2052.07     768 2057.93   787.8 2065.94   807.5 2070.06   846.9 2071.51
#Mann= 3 , 0 , 0
       0      .1       0   435.5    .045       0   447.5      .1       0
Bank Sta=435.5,447.5
XS Rating Curve= 0 ,0
Exp/Cntr=0.3,0.1

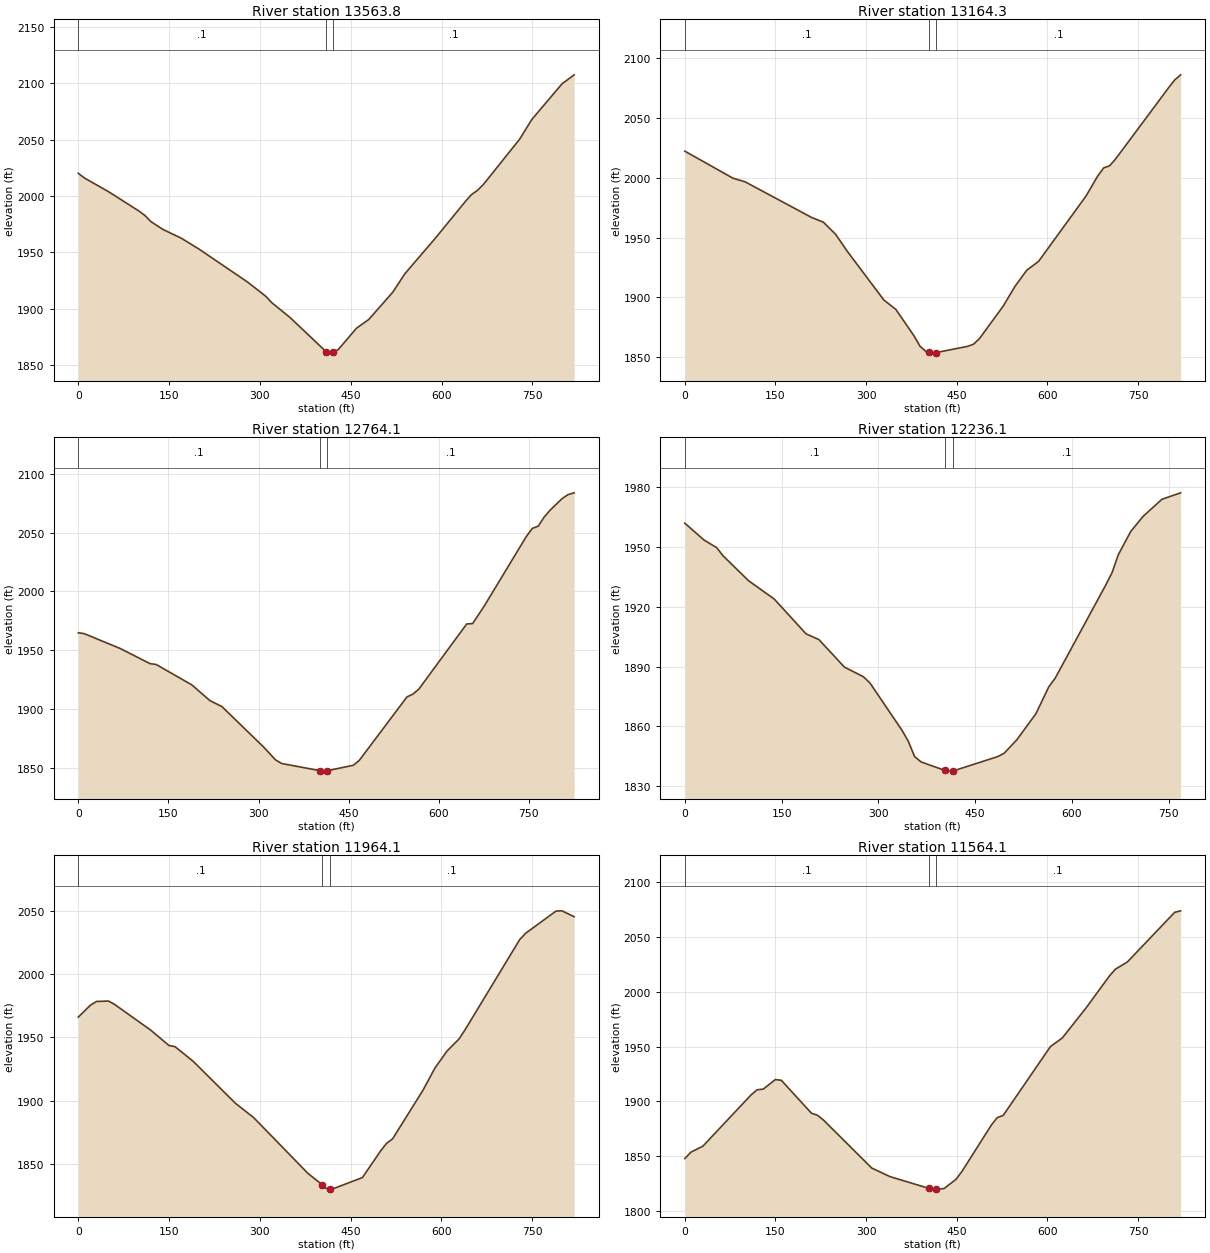
Type RM Length L Ch R = 1 ,13563.8 ,404,399.2,392.4
XS GIS Cut Line= 3
     1990893.909      122748.948      1991218.83      122499.484
     1991549.463      122257.923
#Sta/Elev= 30
       0 2020.15      10 2016.03      50  2003.8    99.9 1986.73   109.9 1982.78
   119.9 1977.27   139.9 1970.28   169.8 1962.63   199.8 1952.72   279.8 1923.51
   309.7 1910.96   319.7 1905.22   349.7 1892.16   409.4 1861.74   419.6  1860.5
   421.4 1861.09   429.6 1863.76   459.6 1882.66   479.6 1890.28   519.5  1914.6
   539.5 1931.03   589.4 1962.29   639.4 1995.15   649.3 2001.19   659.3 2004.96
   669.3 2010.32   729.2 2050.55   749.2 2067.98   799.1 2099.59   819.1 2107.58
#Mann= 3 , 0 , 0
       0      .1       0   409.4    .045       0   421.4      .1       0
Bank Sta=409.4,421.4
XS Rating Curve= 0 ,0
Exp/Cntr=0.3,0.1

Type RM Length L Ch R = 1 ,13164.3 ,403.6,400.4,395.1
XS GIS Cut Line= 3
     1991225.084      123101.272     1991490.906      122790.204
     1991730.323      122455.719
#Sta/Elev= 30
       0 2022.19    79.8 1999.56    99.8 1996.56   209.6 1966.82   229.5 1962.75
   249.5 1952.71   269.5 1938.06   329.3 1897.81   349.3 1889.86   379.2 1867.86
   389.2 1859.17   399.2  1854.6   404.2 1853.97   409.2 1853.34   416.2 1853.82
   467.9 1859.01   477.7 1860.78   487.5  1865.4   526.7 1892.49   546.3 1909.06
   565.9 1922.66   585.5 1930.08   663.8 1984.55   683.4 2001.48   693.2  2008.2
     703 2009.97   712.8 2015.57   800.9 2075.41   810.7 2081.72   820.5 2085.99
#Mann= 3 , 0 , 0
       0      .1       0   404.2    .045       0   416.2      .1       0
Bank Sta=404.2,416.2
XS Rating Curve= 0 ,0
Exp/Cntr=0.3,0.1

Type RM Length L Ch R = 1 ,12764.1 ,518.8,527.9,540.9
XS GIS Cut Line= 3
      1991633.51      123320.193     1991846.201      122971.947
     1991996.057      122582.368
#Sta/Elev= 30
       0 1964.84      10 1964.04    69.7 1951.46   119.4 1938.56   129.4 1937.91
   189.1 1920.49     219 1907.16   238.9 1902.13   308.5 1867.68   328.4 1856.74
   338.4 1853.69   402.1 1847.62   408.1 1847.19   414.1 1847.52   457.8 1852.16
   467.7 1856.29   547.2 1910.31   557.1 1912.67   567.1 1917.05   646.6  1972.3
   656.5 1972.65   676.4 1988.05     746 2046.78   755.9 2053.56   765.8  2055.5
   775.8 2063.33   785.7 2069.19   805.6 2078.98   815.5 2082.31   825.5  2083.8
#Mann= 3 , 0 , 0
       0      .1       0   402.1    .045       0   414.1      .1       0
Bank Sta=402.1,414.1
XS Rating Curve= 0 ,0
Exp/Cntr=0.3,0.1

Type RM Length L Ch R = 1 ,12236.1 ,279.7,272,264.1
XS GIS Cut Line= 3
     1991931.603      123424.748     1992460.091       123076.37
     1992555.011      122980.132
#Sta/Elev= 30
       0 1961.81    29.7 1953.38    49.4 1949.54    59.3 1945.45    98.9 1932.96
   138.5 1923.82   187.9 1906.35   207.7 1903.52   247.3 1889.72   276.9 1884.84
   286.8 1881.78   336.3 1858.17   346.2 1852.62     356 1844.93   365.9 1842.24
     403 1837.94     415  1837.6   484.6 1844.86   494.5 1846.48   514.3 1853.24
     544 1866.36   563.8 1879.74   573.6 1884.01   652.3 1930.88     662 1937.04
   671.6 1945.96   690.9 1957.64   710.2 1965.25   739.2 1973.76   768.2    1977
#Mann= 3 , 0 , 0
       0      .1       0     403    .045       0     415      .1       0
Bank Sta=403,415
XS Rating Curve= 0 ,0
Exp/Cntr=0.3,0.1

Type RM Length L Ch R = 1 ,11964.1 ,407.6,400.1,394.4
XS GIS Cut Line= 3
     1992226.969      123721.455     1992465.439       123388.67
     1992699.147      123052.116
#Sta/Elev= 30
       0 1966.05      20 1975.44      30 1978.34    49.9 1978.66    59.9 1976.03
   119.8 1955.68   149.8 1943.62   159.8 1942.71   189.7  1931.2   259.6 1898.05
   289.6 1886.82   379.4 1842.77   403.4 1833.69   409.4 1830.94   415.4  1830.6
   419.4 1830.38   469.4 1839.52   499.4 1860.49   509.3 1866.48   519.3 1870.08
   569.3 1908.26   589.3 1925.96   609.3 1939.32   629.3 1948.94   639.3 1956.26
   729.2 2027.11   739.2 2032.17   789.2  2049.6   799.2 2049.81   819.2 2045.15
#Mann= 3 , 0 , 0
       0      .1       0   403.4    .045       0   415.4      .1       0
Bank Sta=403.4,415.4
XS Rating Curve= 0 ,0
Exp/Cntr=0.3,0.1

Type RM Length L Ch R = 1 ,11564.1 ,393.5,399.6,405.4
XS GIS Cut Line= 3
     1992693.201      123993.632     1992800.876      123598.822
     1992939.771      123211.967
#Sta/Elev= 30
       0 1847.93      10 1853.73    29.9 1859.24   109.8 1906.07   119.8 1910.69
   129.8 1911.23   149.7 1919.96   159.7 1919.31   209.6 1889.27   219.6  1887.4
   229.6 1882.95   309.4 1839.26   339.4  1831.5   403.2 1820.88   415.2  1820.1
     419 1820.08   428.8 1820.61   448.4 1828.87   458.2 1835.93   507.1 1878.44
   516.9 1885.31   526.7 1887.24     605 1950.11   624.5 1957.87   663.7 1985.15
   702.8 2014.63   712.6 2020.69   732.2 2027.18   810.5 2072.47   820.3 2073.81
#Mann= 3 , 0 , 0
       0      .1       0   403.2    .045       0   415.2      .1       0
Bank Sta=403.2,415.2
XS Rating Curve= 0 ,0
Exp/Cntr=0.3,0.1

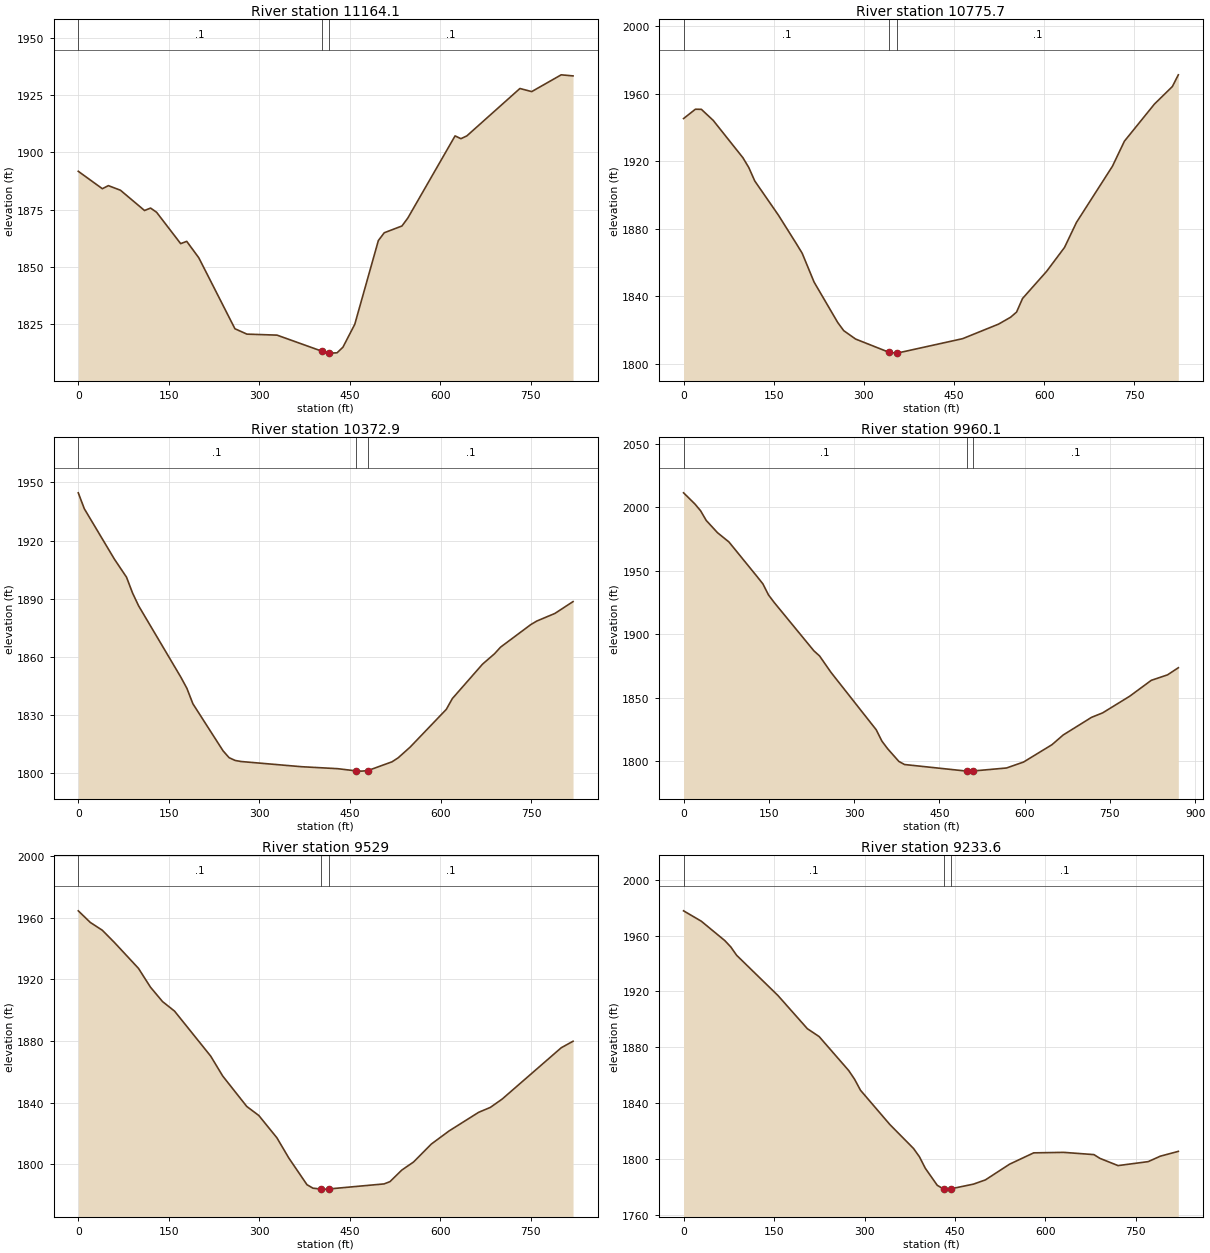
Type RM Length L Ch R = 1 ,11164.1 ,375.2,388.3,400.1
XS GIS Cut Line= 3
      1992939.89      124112.917     1993156.755      123765.776
     1993395.272      123431.605
#Sta/Elev= 30
       0 1891.76    39.9 1884.16    49.9  1885.5    69.9 1883.49   109.8 1874.64
   119.8  1875.7   129.8 1873.86   169.7 1860.16   179.7 1861.17   199.7    1854
   259.6 1822.99   279.5 1820.64   329.4  1820.2   403.3 1813.22   415.3 1812.57
   419.1 1812.34   428.9 1812.49   438.6 1814.94   458.2 1824.94   497.3 1861.52
   507.1 1864.92   536.4 1867.88   546.2 1871.38   624.4 1907.22   634.1 1906.01
   643.9 1907.22   731.9 1927.93   751.4 1926.57   800.3  1933.9   819.9 1933.43
#Mann= 3 , 0 , 0
       0      .1       0   403.3    .045       0   415.3      .1       0
Bank Sta=403.3,415.3
XS Rating Curve= 0 ,0
Exp/Cntr=0.3,0.1

Type RM Length L Ch R = 1 ,10775.7 ,401.5,402.8,404.6
XS GIS Cut Line= 3
     1993031.293      124208.543     1993415.002      124052.032
     1993808.878      123943.198
#Sta/Elev= 30
       0 1945.39    19.7 1950.92    29.6 1950.86    49.3  1944.3    98.7 1922.17
   108.5 1916.35   118.4  1908.4   157.9 1888.05   187.5 1871.26   197.3 1865.54
   217.1 1848.44   256.5 1824.44   266.4 1819.65   286.1 1814.68   342.4 1806.72
   354.4 1806.33   355.2 1806.32   464.2 1814.89     524 1823.52     544  1827.6
   553.9 1830.64   563.9 1838.73   603.8 1854.76   633.7 1868.98   653.6 1883.85
   713.4 1917.11   733.3 1931.96   783.2 1953.95   813.1 1964.37     823 1971.31
#Mann= 3 , 0 , 0
       0      .1       0   342.4    .045       0   354.4      .1       0
Bank Sta=342.4,354.4
XS Rating Curve= 0 ,0
Exp/Cntr=0.3,0.1

Type RM Length L Ch R = 1 ,10372.9 ,419.5,412.8,405.7
XS GIS Cut Line= 3
     1993131.217      124566.822     1993519.685      124437.333
      1993910.84      124315.786
#Sta/Elev= 30
       0 1944.62      10 1936.41    59.9 1910.39    79.9 1901.11    89.9 1892.93
    99.9 1886.36   169.8 1849.59   179.8 1843.84   189.8 1835.84   239.7 1811.61
   249.7 1808.07   259.7 1806.64   269.7 1806.09   369.5 1803.42   429.5  1802.4
   459.4 1801.28   469.4 1801.14   479.4 1801.42   519.4 1805.94   529.4 1807.95
   549.4 1813.52   609.3 1832.99   619.3 1838.55   669.2 1856.27   689.2 1861.68
   699.2 1865.08   749.2 1876.69   759.1 1878.52   789.1 1882.44   819.1 1888.54
#Mann= 3 , 0 , 0
       0      .1       0   459.4    .045       0   479.4      .1       0
Bank Sta=459.4,479.4
XS Rating Curve= 0 ,0
Exp/Cntr=0.3,0.1

Type RM Length L Ch R = 1 ,9960.1  ,434.8,431,427.3
XS GIS Cut Line= 3
     1993347.331      125067.058     1993932.672      124634.644
     1993997.197       124507.43
#Sta/Elev= 30
       0  2011.4    19.9 2002.63    29.9 1997.28    39.9 1989.61    59.8 1979.92
    79.8 1972.68   129.6 1945.24   139.6  1939.6   149.5 1930.85   159.5 1924.92
   229.3 1886.83   239.3 1882.78   259.2 1869.95     339 1824.56   348.9 1815.69
   358.9 1809.72   378.8 1799.65   388.8 1797.21   498.4 1792.01   508.4 1792.08
   568.2 1794.49   598.1 1799.17     648 1812.81   667.9 1820.52   717.8 1834.43
   737.2 1837.92   784.8 1851.03   822.8 1863.58   851.4  1867.9   870.4 1873.51
#Mann= 3 , 0 , 0
       0      .1       0   498.4    .045       0   508.4      .1       0
Bank Sta=498.4,508.4
XS Rating Curve= 0 ,0
Exp/Cntr=0.3,0.1

Type RM Length L Ch R = 1 ,9529    ,289.7,295.4,301
XS GIS Cut Line= 3
     1993719.582      125414.041     1993999.241      125115.452
     1994281.605      124816.524
#Sta/Elev= 30
       0 1964.55      20 1956.99    39.9 1951.92    59.9    1944    99.8 1927.18
   119.7 1914.95   139.7 1905.59   159.6 1899.39   219.5 1870.18   239.5 1857.21
   279.4 1837.43   299.3 1831.59   329.3  1817.1   349.2 1803.88   379.2 1786.61
   389.2 1784.34   402.9 1783.78   409.1 1783.74   414.9 1783.83     507 1787.13
   516.8 1788.61   536.4 1796.12     556  1801.4   585.3 1813.01   614.7 1821.52
   663.7 1833.62   683.2 1836.84   702.8 1842.24   800.7 1875.58   820.3 1879.82
#Mann= 3 , 0 , 0
       0      .1       0   402.9    .045       0   414.9      .1       0
Bank Sta=402.9,414.9
XS Rating Curve= 0 ,0
Exp/Cntr=0.3,0.1

Type RM Length L Ch R = 1 ,9233.6  ,458.9,455.7,452.1
XS GIS Cut Line= 3
     1993806.896      125593.559     1994147.888        125364.9
      1994497.54      125151.233
#Sta/Elev= 30
       0 1977.65    29.3 1970.26    68.4 1956.37    78.2 1951.88      88 1945.87
   156.4 1917.15   205.3 1893.37   224.8 1887.75   273.7 1863.53   283.5 1857.28
   293.3 1849.42   342.1 1824.85   381.2  1807.8     391 1801.89   400.8 1793.62
   420.6 1781.45     431 1778.81   440.5 1778.71     443 1778.92   480.5 1782.27
   500.5 1785.32   540.5 1796.54   580.5 1804.64   630.4 1804.99   680.4 1803.38
   690.4 1800.68   720.4 1795.53   770.4 1798.37   790.4 1802.26   820.3  1805.7
#Mann= 3 , 0 , 0
       0      .1       0     431    .045       0     443      .1       0
Bank Sta=431,443
XS Rating Curve= 0 ,0
Exp/Cntr=0.3,0.1

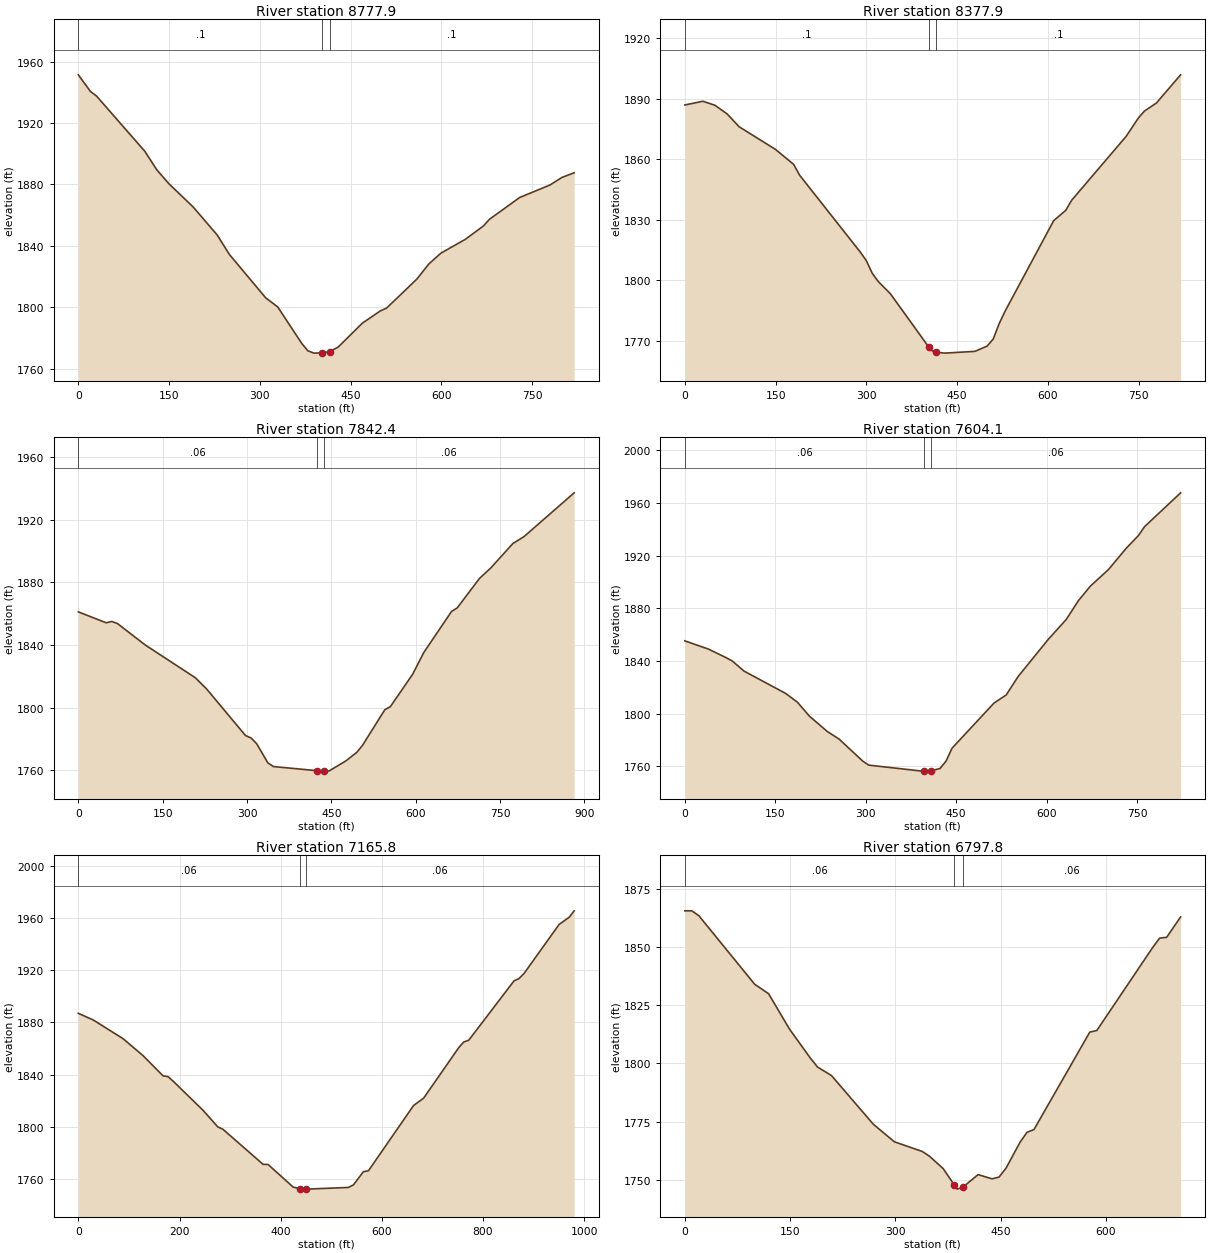
Type RM Length L Ch R = 1 ,8777.9  ,400.1,400,400.3
XS GIS Cut Line= 3
     1994112.271      125988.745     1994425.434      125725.142
     1994733.299      125454.441
#Sta/Elev= 30
       0 1951.45      20 1940.63      30 1937.66   109.8 1901.66   129.8  1889.5
   149.8 1880.44   189.7 1865.38   229.6 1847.02   249.6 1834.43   309.5  1806.2
   329.5 1800.21   369.4 1776.34   379.4 1771.63   389.4 1770.13   403.3 1770.29
   415.3 1771.07   429.3 1774.07   469.3 1789.64   499.3 1797.71   509.3 1799.45
   559.3 1818.33   579.3 1828.27   599.3 1835.31   639.3 1844.23   669.3 1852.96
   679.3 1857.32   729.3 1871.54   779.3 1879.66   799.3 1884.63   819.3 1887.63
#Mann= 3 , 0 , 0
       0      .1       0   403.3    .045       0   415.3      .1       0
Bank Sta=403.3,415.3
XS Rating Curve= 0 ,0
Exp/Cntr=0.3,0.1

Type RM Length L Ch R = 1 ,8377.9  ,539,535.5,532
XS GIS Cut Line= 3
     1994392.758      126276.457     1994703.666      126009.949
     1995014.574      125743.442
#Sta/Elev= 30
       0 1886.84      30 1888.69    49.9 1886.68    69.9 1882.41    89.9 1876.02
   149.8 1864.83   179.8 1857.41   189.8 1851.99   289.6 1814.06   299.6 1809.85
   309.6 1803.47   319.6 1799.35   339.6  1793.3   403.5 1766.68   409.5 1764.81
   415.5 1764.31   429.5 1763.88   479.4 1764.76   499.4 1767.38   509.4 1770.83
   519.4 1778.57   529.4 1784.86   609.3 1829.51   629.2 1834.63   639.2  1839.7
   729.1 1871.32   749.1 1880.35   759.1  1883.8     779 1887.81     819 1901.78
#Mann= 3 , 0 , 0
       0      .1       0   403.5    .045       0   415.5      .1       0
Bank Sta=403.5,415.5
XS Rating Curve= 0 ,0
Exp/Cntr=0.3,0.1

Type RM Length L Ch R = 1 ,7842.4  ,236.3,238.1,241.2
XS GIS Cut Line= 3
     1994822.293      126677.413     1995165.317      126266.744
     1995359.112      125979.347
#Sta/Elev= 30
       0 1861.14    49.5 1854.19    59.4 1855.03    69.4 1853.76   118.9 1840.04
   208.1 1819.12   227.9 1812.05   297.3 1782.25   307.2 1780.68   317.1 1777.05
   336.9 1764.89   346.8 1762.46   424.5 1759.82     436 1759.54   436.5 1759.55
   445.9 1759.64   475.6 1766.03   495.4 1771.59   505.4 1776.02     545 1798.71
   554.9 1800.69   594.5 1821.34   614.3 1835.21   663.8 1861.48   673.7 1863.65
   713.4 1882.51   733.2 1889.08   772.8 1904.76   792.6 1909.19   881.7  1937.1
#Mann= 3 , 0 , 0
       0     .06       0   424.5    .045       0   436.5     .06       0
Bank Sta=424.5,436.5
XS Rating Curve= 0 ,0
Exp/Cntr=0.3,0.1

Type RM Length L Ch R = 1 ,7604.1  ,449.6,438.3,425.8
XS GIS Cut Line= 3
     1994974.033      126807.334     1995264.946      126514.009
     1995585.628      126260.374
#Sta/Elev= 30
       0 1855.41    39.4 1849.11    68.8 1842.56    78.7  1840.1    98.4 1832.37
   167.2 1815.46   186.9 1808.72   206.6 1798.22   236.1  1786.6   255.7 1780.82
   295.1 1764.01   304.9 1761.01   393.4 1756.44   396.3 1756.48   408.3 1756.73
   423.1 1758.43   433.1 1764.03     443 1773.83   512.8 1808.23   532.8 1814.27
   552.7 1828.36   602.6 1856.54   632.5 1871.72   652.5 1885.92   672.4 1896.98
   702.3  1909.5   732.2 1925.93   752.2 1935.45   762.2 1942.14     822 1967.84
#Mann= 3 , 0 , 0
       0     .06       0   396.3    .045       0   408.3     .06       0
Bank Sta=396.3,408.3
XS Rating Curve= 0 ,0
Exp/Cntr=0.3,0.1

Type RM Length L Ch R = 1 ,7165.8  ,371.3,367,362.7
XS GIS Cut Line= 3
     1995399.981       127268.68     1995481.718      127015.559
     1995672.876      126327.388
#Sta/Elev= 30
       0 1887.05    29.6 1881.91    88.7 1867.51   128.1 1854.47   167.5 1839.03
   177.3 1838.42   187.2 1835.02   246.3 1812.67   275.9 1799.76   285.8 1798.01
   365.2 1771.07   375.1 1770.96   424.7  1753.6   438.7 1752.24   450.7 1752.02
   533.8 1753.31   543.8 1755.28   563.6 1765.43   573.5  1766.1   662.8 1816.27
   682.6 1821.87   752.1 1860.71     762 1865.02   771.9 1866.42   861.2 1911.92
   871.1 1913.72     881 1917.58   950.5 1955.32   970.3 1960.79   980.2 1965.76
#Mann= 3 , 0 , 0
       0     .06       0   438.7    .045       0   450.7     .06       0
Bank Sta=438.7,450.7
XS Rating Curve= 0 ,0
Exp/Cntr=0.3,0.1

Type RM Length L Ch R = 1 ,6797.8  ,453.4,455.9,458.3
XS GIS Cut Line= 2
     1995855.432      127303.711     1995904.904      126598.965
#Sta/Elev= 30
       0 1865.48      10 1865.48    19.9 1863.44    99.5 1833.99   119.4  1829.9
   149.3 1814.67   179.1 1802.19   189.1 1798.45     209 1794.78   268.7 1773.87
   298.5 1766.36   338.3  1762.2   348.3 1760.24   368.2 1754.83   384.2 1747.72
   388.1 1746.03   396.2 1746.85   417.9 1752.26   437.8 1750.45   447.8 1751.21
   457.7 1755.02   477.6  1766.1   487.6 1770.42   497.5 1771.58   577.1 1813.43
   587.1 1814.12   666.7 1849.74   676.6 1853.77   686.6 1854.11   706.5 1862.86
#Mann= 3 , 0 , 0
       0     .06       0   384.2    .045       0   396.2     .06       0
Bank Sta=384.2,396.2
XS Rating Curve= 0 ,0
Exp/Cntr=0.3,0.1

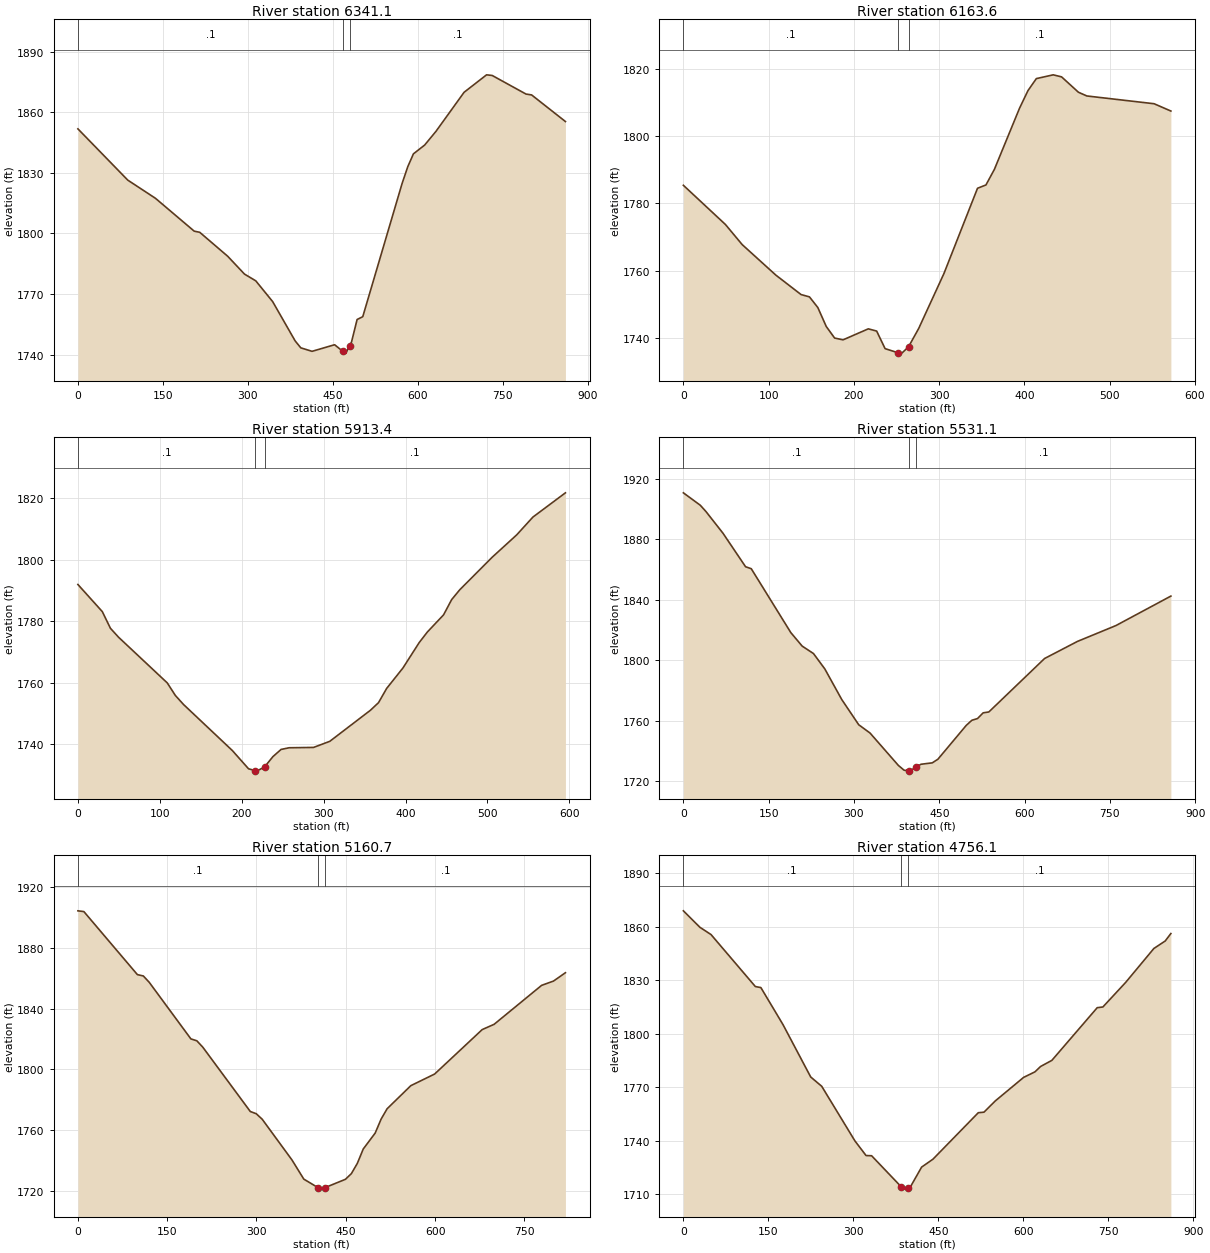
Type RM Length L Ch R = 1 ,6341.1  ,172.7,177.4,182.1
XS GIS Cut Line= 3
     1996128.988       127282.89     1996235.806       127063.02
      1996367.88      126461.099
#Sta/Elev= 30
       0  1851.8      88 1826.41   136.9  1817.4   205.3 1801.12   215.1 1800.55
   264.3 1788.72   294.1 1779.84     314 1776.51   343.8 1766.22   383.6 1746.71
   393.5  1743.3   413.4 1741.57   453.2 1744.84   467.6  1741.6     473 1740.68
   479.6 1744.27     483 1746.12   492.9 1757.34   502.9 1758.73   572.4  1824.8
   582.4 1833.07   592.3 1839.41   612.2 1843.79   632.1 1850.56   681.8 1869.93
   721.5 1878.58   731.5 1878.25   791.1 1869.05     801 1868.62   860.7 1855.44
#Mann= 3 , 0 , 0
       0      .1       0   467.6    .045       0   479.6      .1       0
Bank Sta=467.6,479.6
XS Rating Curve= 0 ,0
Exp/Cntr=0.3,0.1

Type RM Length L Ch R = 1 ,6163.6  ,229.9,249.9,269.9
XS GIS Cut Line= 2
     1996341.479      127133.149     1996584.835      126615.733
#Sta/Elev= 30
       0 1785.43    49.3 1773.75      69 1767.74   108.4 1758.66     138 1752.85
   147.9 1752.15   157.7 1748.98   167.6 1743.32   177.4 1739.88   187.3 1739.34
   216.9 1742.62   226.7 1741.96   236.6 1736.72   252.2 1735.45   256.3 1735.38
   264.2 1737.31     276 1742.73   305.6  1759.1     345 1784.54   354.9 1785.53
   364.8 1790.18   394.3 1808.42   404.2 1813.67     414 1817.24   433.8 1818.37
   443.6 1817.76   463.4 1813.17   473.2 1812.07   552.1 1809.75   571.8 1807.57
#Mann= 3 , 0 , 0
       0      .1       0   252.2    .045       0   264.2      .1       0
#XS Ineff= 2 , 0
           217.1 1742.51
Permanent Ineff=
       F       F
Bank Sta=252.2,264.2
XS Rating Curve= 0 ,0
Exp/Cntr=0.3,0.1

Type RM Length L Ch R = 1 ,5913.4  ,403.6,382.2,360.8
XS GIS Cut Line= 2
     1996330.726      127155.303     1996913.431      127034.016
#Sta/Elev= 30
       0    1792    29.8 1783.18    39.7 1777.76    49.6 1774.86   109.1 1759.99
     119  1755.9     129 1752.96   188.5 1738.01   208.3 1732.07   215.8 1731.49
   218.2  1731.3   227.8 1732.64   238.1 1736.02     248 1738.35   257.9  1738.9
   287.7 1739.01   307.5 1740.99   357.1 1751.09     367 1753.57     377 1758.22
   396.8 1764.84   416.6 1773.08   426.6 1776.54   446.4 1782.12   456.3 1787.09
   466.2 1790.29   505.9  1800.9   535.7 1808.14   555.5 1813.93   595.2 1821.82
#Mann= 3 , 0 , 0
       0      .1       0   215.8    .045       0   227.8      .1       0
Bank Sta=215.8,227.8
XS Rating Curve= 0 ,0
Exp/Cntr=0.3,0.1

Type RM Length L Ch R = 1 ,5531.1  ,376,370.4,364.8
XS GIS Cut Line= 3
      1996620.64      127780.742     1996831.694      127233.085
     1997000.767      127022.093
#Sta/Elev= 30
       0 1910.57    29.8 1902.34    39.8 1898.16    69.6 1883.88   109.4 1861.68
   119.4 1860.38     189 1818.11   208.9 1809.21   228.8 1804.28   248.7 1794.14
   278.5 1773.89   308.4 1757.18   328.3  1751.7     378 1730.33     388 1727.16
   397.3 1726.56   397.9 1726.52   409.3 1729.19   417.8 1731.06   437.7 1731.99
   447.6 1734.39   497.4 1756.75   507.3 1760.14   517.3  1761.3   527.2 1765.07
   537.2 1765.65   635.2    1801   693.1 1812.32   760.7 1822.79   857.3 1842.28
#Mann= 3 , 0 , 0
       0      .1       0   397.3    .045       0   409.3      .1       0
Bank Sta=397.3,409.3
XS Rating Curve= 0 ,0
Exp/Cntr=0.3,0.1

Type RM Length L Ch R = 1 ,5160.7  ,411.4,404.5,396.7
XS GIS Cut Line= 3
     1997090.258      127870.564     1997131.068      127463.102
     1997171.877      127055.641
#Sta/Elev= 30
       0 1904.42      10 1903.92    99.9 1862.38   109.9 1861.49   119.8 1857.31
   189.8 1820.01   199.8 1818.76   209.7 1814.61   289.6 1772.16   299.6 1770.69
   309.6 1767.07   359.6 1740.23   379.5 1727.59   403.5 1721.96   409.5    1721
   415.5 1722.06   449.4 1727.47   459.4 1731.22   469.4 1737.98   479.4 1747.48
   499.4 1757.95   509.4 1767.16   519.4 1773.95   559.3  1789.2   599.3 1796.86
   679.2 1826.15   699.2 1829.62     779  1855.3     799 1858.13     819 1863.62
#Mann= 3 , 0 , 0
       0      .1       0   403.5    .045       0   415.5      .1       0
Bank Sta=403.5,415.5
XS Rating Curve= 0 ,0
Exp/Cntr=0.3,0.1

Type RM Length L Ch R = 1 ,4756.1  ,437.4,418.4,401.3
XS GIS Cut Line= 3
     1997615.104      127893.513     1997524.153      127503.445
     1997382.704      127065.898
#Sta/Elev= 30
       0  1868.8    29.3 1859.55    48.8  1855.5     127 1826.38   136.8 1825.78
   175.8 1805.06   224.7  1775.7   244.2 1770.46   302.8 1739.85   322.4 1731.66
   332.2 1731.55   384.1 1714.28   390.8 1712.84   396.1 1713.47   400.5    1714
   420.5 1725.19   440.5 1729.62   520.5 1755.66   530.5 1755.96   550.5 1762.27
   600.5 1775.46   620.5 1778.56   630.4 1781.56   650.4 1785.01   730.4 1814.52
   740.4 1814.92   780.4 1828.61   830.4  1847.7   850.4  1851.9   860.4 1856.08
#Mann= 3 , 0 , 0
       0      .1       0   384.1    .045       0   396.1      .1       0
Bank Sta=384.1,396.1
XS Rating Curve= 0 ,0
Exp/Cntr=0.3,0.1