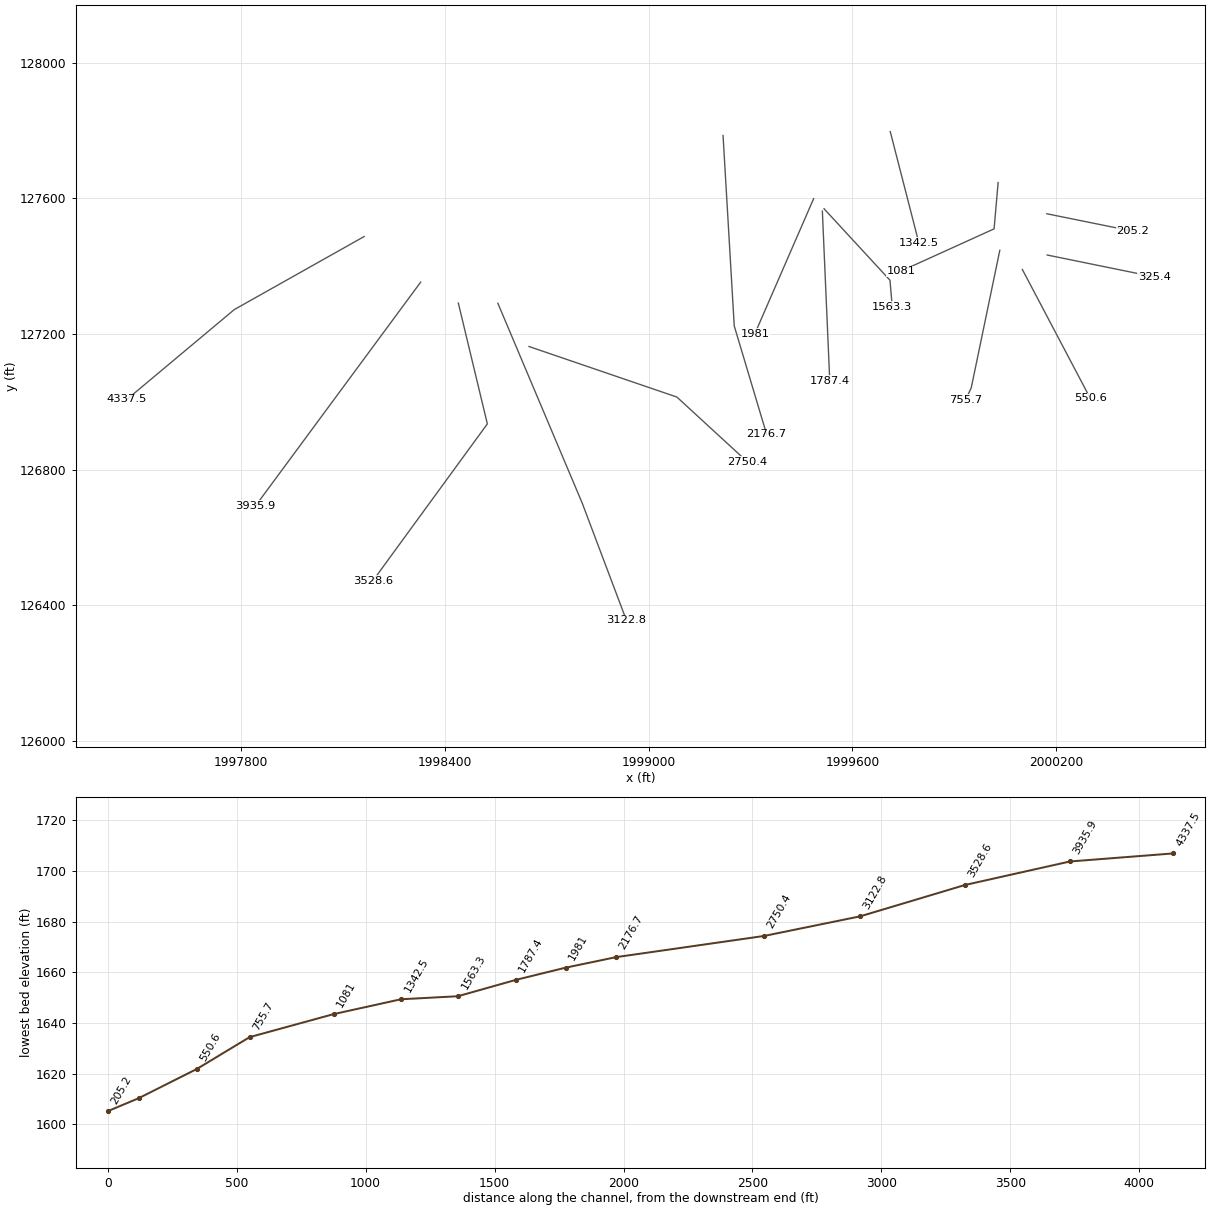
HEC-RAS study BgSprngBr.prj: BgSprngBr

--- BgSprngBr.g01 (geometry) --- (continued)

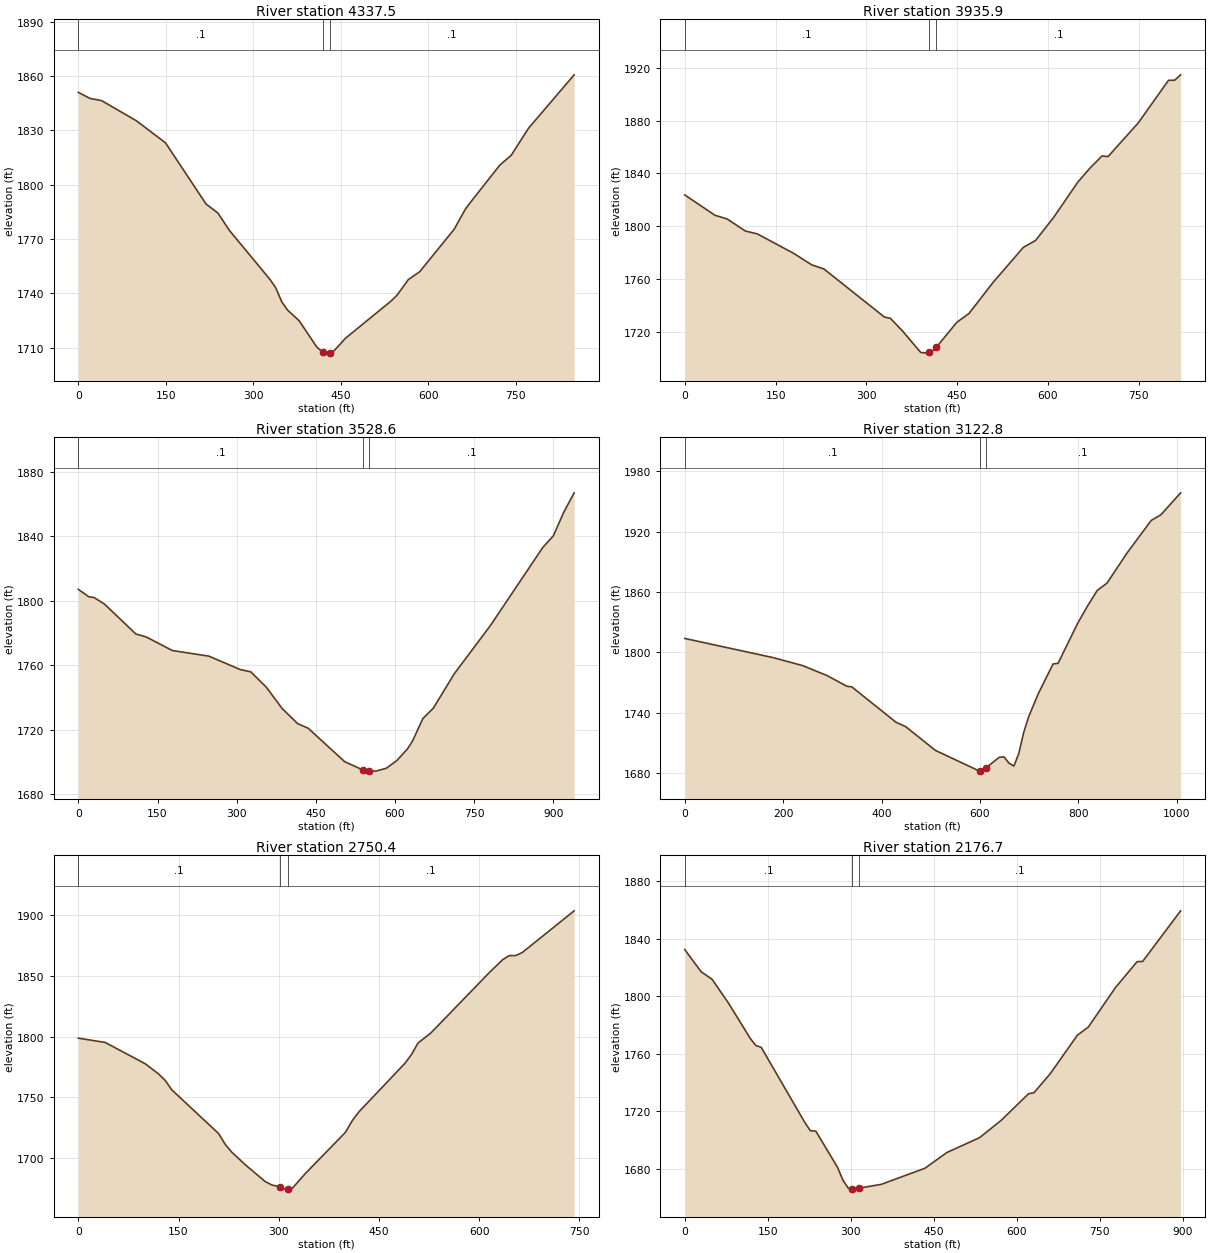
Type RM Length L Ch R = 1 ,4337.5  ,392.3,401.6,409.3
XS GIS Cut Line= 3
     1998163.294      127487.478     1997781.289      127272.161
     1997465.641      127007.543
#Sta/Elev= 30
       0 1850.94    19.9 1847.59    39.9 1846.36    99.7 1835.21   149.5 1823.05
   219.2 1789.21   239.2 1784.37   259.1  1774.7   328.9 1747.55   338.8 1742.91
   348.8 1735.35   358.8 1730.71   378.7 1724.85   408.6 1710.47   418.9 1707.43
   428.5 1706.94   430.9 1707.23   438.5 1708.16   458.1 1715.13   536.6 1735.75
   546.4 1738.84     566 1747.54   585.6 1751.93   644.5 1775.28   664.1  1786.6
   673.9 1790.74   722.9 1810.76   742.5  1816.2     772 1831.05   850.4  1860.6
#Mann= 3 , 0 , 0
       0      .1       0   418.9    .045       0   430.9      .1       0
Bank Sta=418.9,430.9
XS Rating Curve= 0 ,0
Exp/Cntr=0.3,0.1

Type RM Length L Ch R = 1 ,3935.9  ,407.1,407.2,407.3
XS GIS Cut Line= 3
       1998329.6      127353.034     1998086.722      127023.336
     1997843.844      126693.639
#Sta/Elev= 30
       0 1823.63    49.9 1808.22    69.9 1805.45    99.9 1796.33   119.8 1794.12
   179.8 1779.39   209.7 1770.64   229.7 1767.58   329.6 1731.14   339.6 1730.13
   359.6 1720.57   389.5 1704.34   399.5 1703.75   403.5 1704.45   409.5 1705.49
   415.5  1708.2   449.4 1727.15   469.4 1733.76   509.4 1757.44   559.3 1783.94
   579.3 1789.09   609.3 1806.65   649.2 1833.36   669.2 1843.96   689.2 1853.18
   699.2 1852.74   749.1 1878.28     799 1910.54     809 1910.57     819 1914.68
#Mann= 3 , 0 , 0
       0      .1       0   403.5    .045       0   415.5      .1       0
Bank Sta=403.5,415.5
XS Rating Curve= 0 ,0
Exp/Cntr=0.3,0.1

Type RM Length L Ch R = 1 ,3528.6  ,384.1,405.8,427.5
XS GIS Cut Line= 3
     1998440.378      127291.282     1998525.756      126935.141
     1998188.395      126471.757
#Sta/Elev= 30
       0 1807.16    19.8 1802.54    29.7 1802.09    49.5 1798.04   108.9 1779.49
   128.7 1777.61   178.2 1769.23   247.4 1765.73   306.8 1757.42   326.6 1756.04
   356.3 1746.44     386 1733.34   415.6  1723.9   435.4 1721.07   504.6 1700.33
   539.4 1695.17   551.4 1694.74   563.9 1694.46   583.6 1696.26   603.4 1701.02
   623.2 1708.07   633.1 1713.06   652.8 1727.07   672.6 1733.48   712.1 1754.73
   781.3 1784.97   880.1 1833.16   899.9 1840.29   919.6 1854.87   939.4 1866.98
#Mann= 3 , 0 , 0
       0      .1       0   539.4    .045       0   551.4      .1       0
Bank Sta=539.4,551.4
XS Rating Curve= 0 ,0
Exp/Cntr=0.3,0.1

Type RM Length L Ch R = 1 ,3122.8  ,354.5,372.4,390.3
XS GIS Cut Line= 3
     1998556.627       127290.89     1998804.734      126701.836
     1998934.656      126356.642
#Sta/Elev= 30
       0 1813.84   179.8 1794.78   239.7 1786.87   289.6  1776.9   329.6 1766.35
   339.6 1765.75   429.4 1730.63   449.4 1726.16   509.3 1702.74   599.2  1682.1
   599.7 1682.19   611.7 1685.02   639.2 1695.88   649.1 1696.16   659.1    1690
   669.1 1687.19     679 1699.61     689 1720.49     699 1736.04   718.9 1759.27
   748.8  1788.6   758.8 1789.11   798.7 1828.86   818.6 1845.95   838.5 1861.49
   858.5 1868.89   898.4 1898.23   948.2 1931.02   968.1 1936.76    1008 1958.44
#Mann= 3 , 0 , 0
       0      .1       0   599.7    .045       0   611.7      .1       0
Bank Sta=599.7,611.7
XS Rating Curve= 0 ,0
Exp/Cntr=0.3,0.1

Type RM Length L Ch R = 1 ,2750.4  ,598.8,573.7,548.6
XS GIS Cut Line= 3
     1998648.361      127163.213     1999083.412      127014.241
     1999291.088      126822.959
#Sta/Elev= 30
       0 1798.68      40 1795.17     100 1777.66     120 1769.27     130 1763.92
     140 1756.05   209.9 1720.18   219.9 1711.23   229.9 1704.66   249.9 1694.45
   279.9 1680.51   289.9 1677.75   301.9 1676.19   309.9 1674.36   313.9 1674.54
   319.9  1674.8   339.9 1687.24   399.9 1721.18   409.9 1730.59   419.9 1737.95
   489.1 1778.08   498.8 1785.27   508.5 1794.69     528 1803.09   615.6 1852.91
   635.1 1863.24   644.8 1866.64   654.6 1866.67   664.3  1869.1   742.2 1903.53
#Mann= 3 , 0 , 0
       0      .1       0   301.9    .045       0   313.9      .1       0
Bank Sta=301.9,313.9
XS Rating Curve= 0 ,0
Exp/Cntr=0.3,0.1

Type RM Length L Ch R = 1 ,2176.7  ,203.7,195.6,185.7
XS GIS Cut Line= 3
     1999219.201      127785.468      1999252.16      127223.857
     1999347.582      126903.891
#Sta/Elev= 30
       0 1832.33    29.6 1816.95    49.4 1811.71      79 1795.18   118.4 1770.66
   128.3 1765.77   138.2 1764.46   217.1 1712.24     227 1706.57   236.9  1706.3
   276.4 1680.97   286.2 1671.99   296.1 1666.45   302.7 1666.15     306    1666
   314.7 1666.66   355.3 1669.32   434.3 1680.52   473.8 1691.42     533 1701.75
   572.4 1713.88   621.5 1732.25   631.3 1732.94   660.8 1746.17   709.9 1772.95
   729.5 1778.51   778.6 1805.93   817.9 1824.01   827.7 1824.09   896.5 1859.28
#Mann= 3 , 0 , 0
       0      .1       0   302.7    .045       0   314.7      .1       0
Bank Sta=302.7,314.7
XS Rating Curve= 0 ,0
Exp/Cntr=0.3,0.1

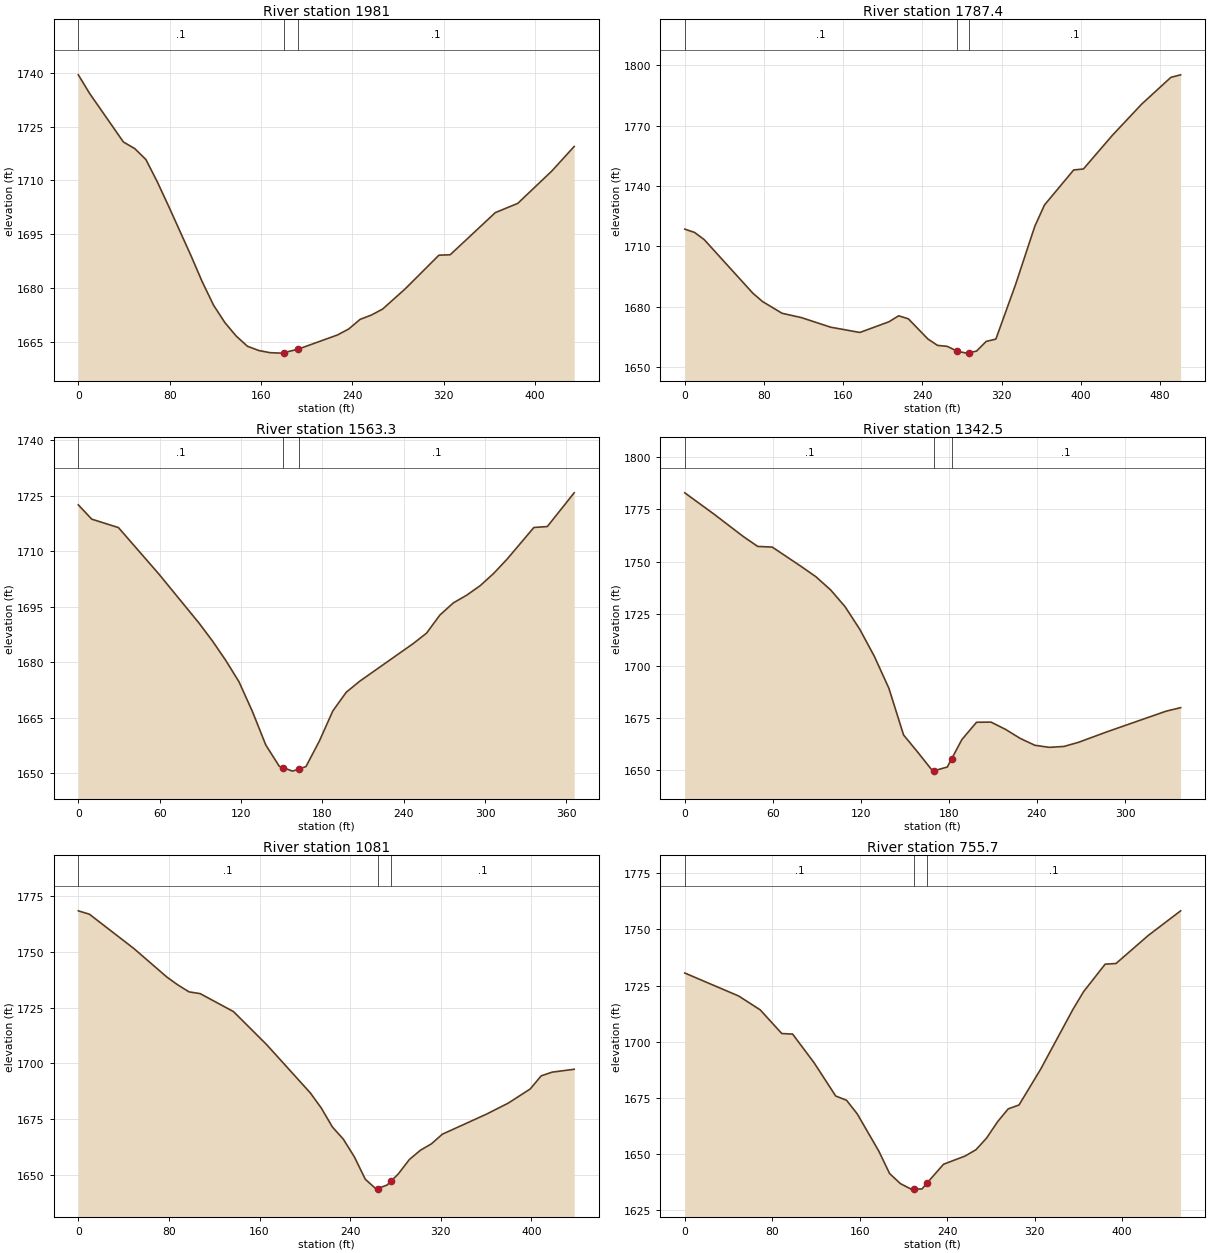
Type RM Length L Ch R = 1 ,1981    ,185.1,193.6,203.9
XS GIS Cut Line= 2
      1999485.67      127599.088     1999312.638      127200.621
#Sta/Elev= 30
       0  1739.4     9.9 1734.21    39.5 1720.68    49.4 1718.85    59.2  1715.8
    69.1 1709.64      79 1702.87    98.7 1689.01   108.6  1681.7   118.5  1675.2
   128.4 1670.36   138.2 1666.64   148.1 1663.78     158 1662.59   167.8 1661.98
   177.7 1661.85   180.1 1661.99   192.1  1662.9   227.1 1666.92     237  1668.6
   246.8 1671.25   256.7 1672.45   266.6 1674.13   286.3 1679.74   315.9 1689.14
   325.8 1689.26   365.3    1701     385 1703.58   414.7 1712.55   434.4 1719.43
#Mann= 3 , 0 , 0
       0      .1       0   180.1    .045       0   192.1      .1       0
Bank Sta=180.1,192.1
XS Rating Curve= 0 ,0
Exp/Cntr=0.3,0.1

Type RM Length L Ch R = 1 ,1787.4  ,207,224.2,240.5
XS GIS Cut Line= 2
     1999511.377      127562.504      1999533.13      127062.196
#Sta/Elev= 30
       0 1718.63     9.8 1717.01    19.6 1713.43    68.7 1686.81    78.6 1682.62
    98.2 1676.82   117.8 1674.66   147.3  1669.9   176.8 1667.28   206.2 1672.59
     216 1675.56   225.8 1674.06   245.5 1664.06   255.3 1660.85   265.1 1660.38
   275.3 1657.92   284.8 1657.01   287.3 1657.26   294.6    1658   304.4 1662.82
   314.2 1663.99   333.8 1690.68   353.5 1720.01   363.3 1730.63   392.8 1748.04
   402.6 1748.51     432 1765.33   461.5 1780.77     491 1794.07   500.8 1795.31
#Mann= 3 , 0 , 0
       0      .1       0   275.3    .045       0   287.3      .1       0
Bank Sta=275.3,287.3
XS Rating Curve= 0 ,0
Exp/Cntr=0.3,0.1

Type RM Length L Ch R = 1 ,1563.3  ,231.6,220.8,210
XS GIS Cut Line= 3
     1999516.321      127569.426     1999710.299      127358.654
     1999717.038      127279.721
#Sta/Elev= 30
       0  1722.5     9.9 1718.64    29.6 1716.36    59.3 1703.86    88.9 1690.62
    98.8  1685.8   108.6 1680.56   118.5 1674.71   128.4 1666.68   138.3 1657.61
   148.2 1651.89   150.7 1651.55     158 1650.57   162.7 1651.15   167.9  1651.8
   177.8 1658.71   187.7 1666.83   197.6 1671.88   207.4 1674.82   246.9    1685
   256.8 1687.84   266.7 1692.74   276.6 1696.02   286.4 1698.09   296.4 1700.67
   306.2 1703.93   316.2 1707.82     336 1716.39   345.9 1716.64   365.7 1725.75
#Mann= 3 , 0 , 0
       0      .1       0   150.7    .045       0   162.7      .1       0
Bank Sta=150.7,162.7
XS Rating Curve= 0 ,0
Exp/Cntr=0.3,0.1

Type RM Length L Ch R = 1 ,1342.5  ,292.2,261.5,230.8
XS GIS Cut Line= 2
     1999711.105      127796.839     1999795.149      127469.562
#Sta/Elev= 30
       0 1782.98    19.9 1772.76    39.8 1762.04    49.7 1757.25    59.6 1756.93
    79.5 1747.55    89.4 1742.67    99.4 1736.36   109.3 1728.26   119.3  1717.4
   129.2 1704.45   139.1 1689.13   149.1 1666.72     159 1658.26     169 1649.37
   169.8 1649.53   178.9 1651.35   181.8  1655.2   188.8  1664.5   198.8 1672.83
   208.7  1672.9   218.6 1669.41   228.6 1665.07   238.5 1661.79   248.4 1660.78
   258.4 1661.22   268.3  1663.2   288.2 1668.37     328 1678.15   337.9 1679.84
#Mann= 3 , 0 , 0
       0      .1       0   169.8    .045       0   181.8      .1       0
Bank Sta=169.8,181.8
XS Rating Curve= 0 ,0
Exp/Cntr=0.3,0.1

Type RM Length L Ch R = 1 ,1081    ,305.3,325.3,345.2
XS GIS Cut Line= 3
     2000028.495      127646.548      2000016.63        127510.1
     1999742.745      127385.518
#Sta/Elev= 30
       0 1768.48     9.8 1766.96    48.9 1751.61    78.3 1738.69      88 1735.16
    97.8 1732.08   107.6 1731.29     137 1723.23   166.1 1708.49   204.9 1686.68
   214.6 1679.86   224.3 1671.44     234 1665.92   243.7 1658.02   253.4 1647.93
   263.1  1643.5   264.5 1643.77   272.8 1645.39   276.5 1647.27   282.6 1650.38
   292.3  1656.8     302 1660.94   311.7 1663.82   321.4 1668.16   360.2 1677.13
   379.6 1682.12     399 1688.48   408.7 1694.38   418.4 1696.04   437.8 1697.33
#Mann= 3 , 0 , 0
       0      .1       0   264.5    .045       0   276.5      .1       0
Bank Sta=264.5,276.5
XS Rating Curve= 0 ,0
Exp/Cntr=0.3,0.1

Type RM Length L Ch R = 1 ,755.7   ,190.2,205.1,220.1
XS GIS Cut Line= 3
     2000033.439       127446.82     1999949.395      127041.432
     1999932.586      127005.837
#Sta/Elev= 30
       0 1730.57    49.3 1720.34      69 1714.16    88.7 1703.64    98.6 1703.41
   118.3  1690.6     138 1675.85   147.9 1673.96   157.7 1667.89   177.4 1651.35
   187.3 1641.35   197.2 1636.85     207 1634.42   209.8 1634.44   216.9 1634.49
   221.8  1637.3   236.6 1645.49   256.3 1649.14   266.2 1651.93     276 1657.15
   285.9 1664.33   295.7 1670.12   305.6 1671.85   325.3 1687.69   354.9 1714.36
   364.7 1722.31   384.4 1734.51   394.3  1734.8   423.8 1747.28   453.4 1758.24
#Mann= 3 , 0 , 0
       0      .1       0   209.8    .045       0   221.8      .1       0
Bank Sta=209.8,221.8
XS Rating Curve= 0 ,0
Exp/Cntr=0.3,0.1

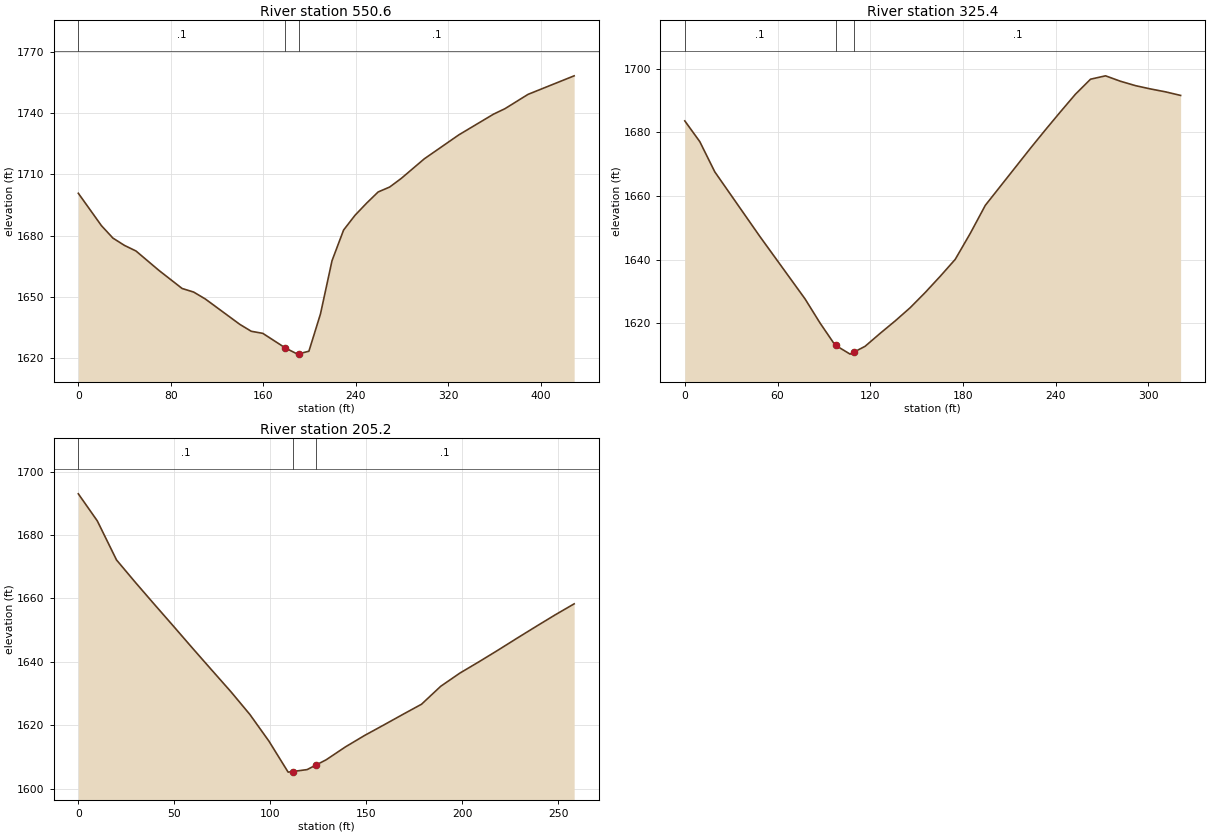
Type RM Length L Ch R = 1 ,550.6   ,205.5,225.2,244.8
XS GIS Cut Line= 2
     2000099.685      127390.461     2000299.413      127010.781
#Sta/Elev= 30
       0 1700.71      20 1684.83    29.9 1678.75    39.9 1675.15    49.9  1672.4
    69.8 1662.86    89.8 1654.02    99.8 1652.26   109.8  1648.9   139.7 1636.44
   149.6 1633.04   159.6 1632.02   179.2 1624.83   189.6 1621.83   191.2 1622.06
   199.5 1623.25   209.5 1641.52   219.5 1667.64   229.5 1682.67   239.4 1689.92
   249.4 1695.85   259.4 1701.35   269.4 1703.78   279.4 1707.99   299.3 1717.59
   329.2 1729.35   359.2  1739.5   369.2 1742.22   389.1 1749.22     429 1758.31
#Mann= 3 , 0 , 0
       0      .1       0   179.2    .045       0   191.2      .1       0
Bank Sta=179.2,191.2
XS Rating Curve= 0 ,0
Exp/Cntr=0.3,0.1

Type RM Length L Ch R = 1 ,325.4   ,120.1,120.1,120.2
XS GIS Cut Line= 2
     2000172.853      127432.978     2000487.276      127368.709
#Sta/Elev= 30
       0 1683.59     9.7 1677.08    19.4 1667.59    48.6 1647.27    77.8 1627.68
    87.5 1620.11    97.2 1613.19    97.6 1613.07     107 1610.31   109.6 1610.97
   116.7 1612.77   126.4 1616.82   136.2 1620.76   145.9 1624.91   155.6 1629.67
   165.3 1634.76     175 1640.07   184.8 1648.28   194.5 1657.06   223.7 1674.99
   233.4 1680.78   243.1 1686.43   252.8 1691.96   262.6 1696.69   272.3 1697.75
     282 1696.04   291.8 1694.65   301.5 1693.62   311.2 1692.71   320.9 1691.59
#Mann= 3 , 0 , 0
       0      .1       0    97.6    .045       0   109.6      .1       0
Bank Sta=97.6,109.6
XS Rating Curve= 0 ,0
Exp/Cntr=0.3,0.1

Type RM Length L Ch R = 1 ,205.2   ,217.7,205.2,192.8
XS GIS Cut Line= 2
     2000171.864      127554.594     2000424.985      127503.179
#Sta/Elev= 29
       0 1692.96     9.9 1684.41    19.9  1672.1    29.8 1664.97    39.7 1658.04
    49.7 1651.12    59.6  1644.2    69.5 1637.38    79.5 1630.53    89.4 1623.34
    99.3 1614.95   109.3 1605.18   111.7 1605.37   119.2 1605.98   123.7 1607.38
   129.1 1609.07   139.1 1613.12     149  1616.7     159 1620.01   168.9 1623.33
   178.8  1626.6   188.8 1632.26   198.7 1636.39   208.6 1639.94   218.6 1643.64
   228.5  1647.4   238.4  1651.1   248.4 1654.78   258.3 1658.26
#Mann= 3 , 0 , 0
       0      .1       0   111.7    .045       0   123.7      .1       0
Bank Sta=111.7,123.7
XS Rating Curve= 0 ,0
Exp/Cntr=0.3,0.1

Chan Stop Cuts=-1
Use User Specified Reach Order=0
Composite Channel Slope=5